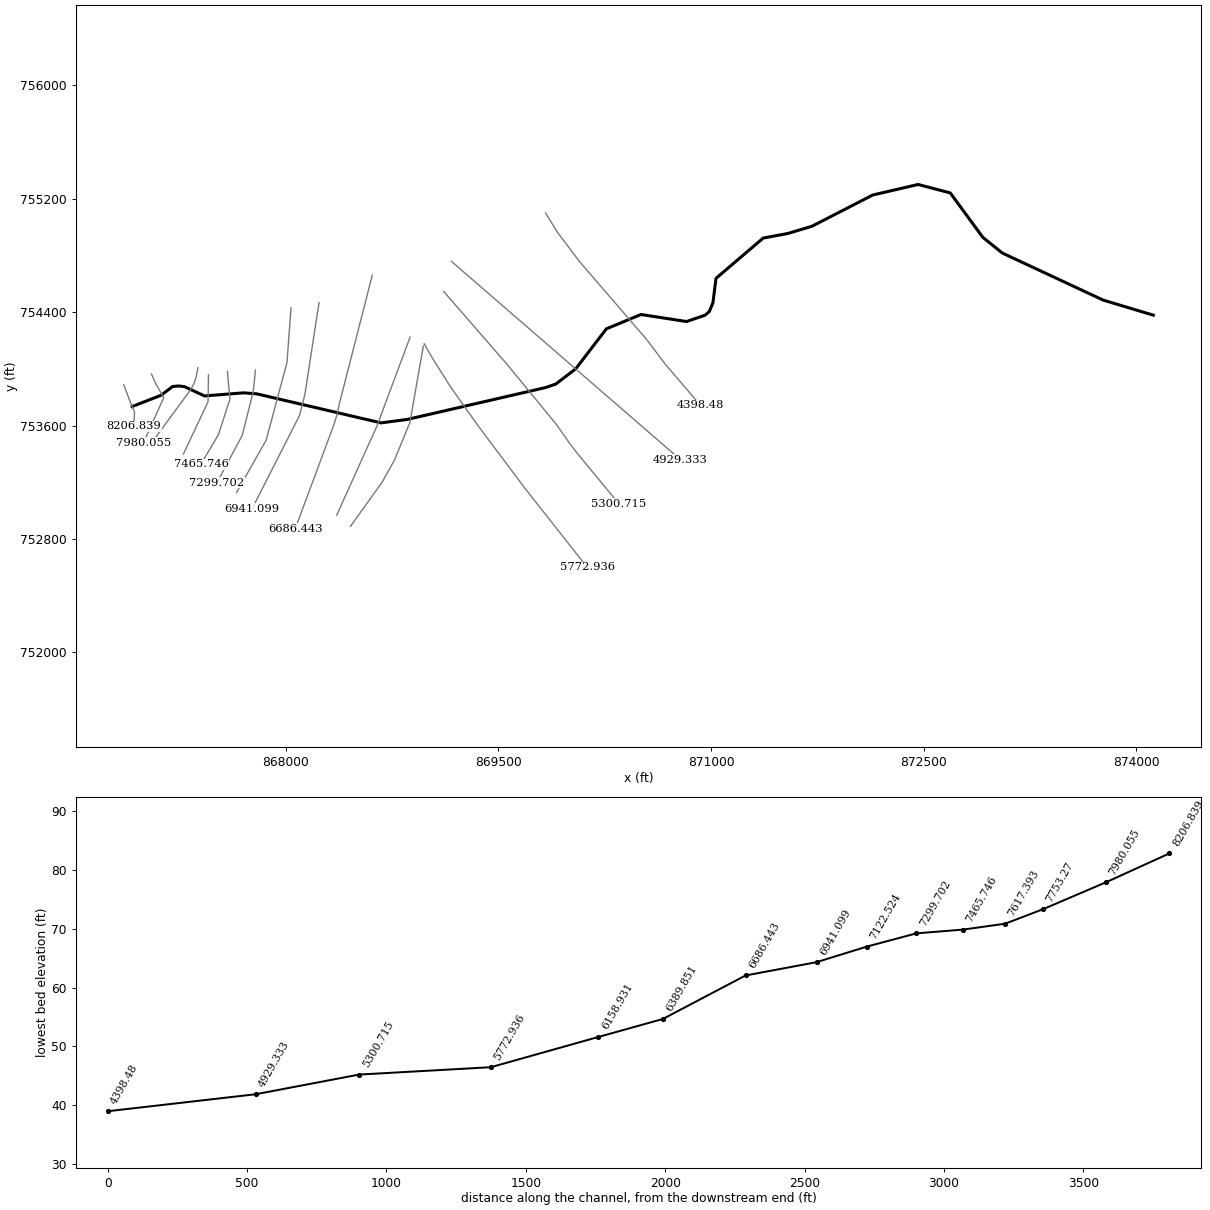
--- 9112_ras.prj (project) ---

Proj Title=9112
Current Plan=p01
Default Exp/Contr=0.3,0.1
English Units
Geom File=g01
Flow File=f01
Plan File=p01
Y Axis Title=Elevation
X Axis Title(PF)=Main Channel Distance
X Axis Title(XS)=Station
BEGIN DESCRIPTION:
RFD model 9112 exported to HEC-RAS
END DESCRIPTION:

--- 9112_ras.p01 (plan) ---

Plan Title=Plan 01
Program Version=4.10
Short Identifier=Plan 01
Geom File=g01
Flow File=f01
Subcritical Flow
Calc Critical at every XS
Secant Critical Depth

--- 9112_ras.f01 (steady flow) ---

Flow Title=Flow 01
Program Version=5.01
Number of Profiles= 6
Profile Names=10yr,25yr,50yr,100yr,100plus,500yr
River Rch & RM=9112,15,8206.839
  169.06  265.21  353.43  431.98  630.69  1074.4
River Rch & RM=9112,15,6158.931
  191.06  300.02  400.13  489.32  714.41 1197.01
River Rch & RM=9112,15,5772.936
  204.28  321.09  428.51   524.3  765.47 1271.46
River Rch & RM=9112,15,5300.715
  209.15  328.86     439  537.24  784.36 1298.94
River Rch & RM=9112,15,4929.333
     220  346.19   462.4  566.12  826.54 1359.95
Boundary for River Rch & Prof#=9112,15,1
Up Type= 0
Dn Type= 2
Boundary for River Rch & Prof#=9112,15,2
Up Type= 0
Dn Type= 2
Boundary for River Rch & Prof#=9112,15,2
Up Type= 0
Dn Type= 2
Boundary for River Rch & Prof#=9112,15,2
Up Type= 0
Dn Type= 2
Boundary for River Rch & Prof#=9112,15,2
Up Type= 0
Dn Type= 2
Boundary for River Rch & Prof#=9112,15,2
Up Type= 0
Dn Type= 2

--- 9112_ras.g01 (geometry) ---

Geom Title=9112
Program Version=4.10

River Reach=9112,15
Reach XY= 30
866915.493021362753733.963153205867121.051204325753813.861510889
867200.866285232753875.022180979867243.183993577753879.362458733
867285.501701911753873.937111598867426.560729672753808.832944889
867701.083299135753830.534333747867792.229132466753824.023917061
868672.365127825753618.670907897868857.014395717753642.973149064
869836.107173225753868.625750162869906.179463587753893.472257524
870046.130732956754000.590445275870261.839472938754282.290958836
870506.500506282754383.340043296870827.547419527754333.707800277
870958.665531085754378.655308644870988.303035391754404.557813074
871013.683657506754465.350214706871035.383086256754638.519216128
871368.689212811754922.669101744871543.552805545754955.254935666
871713.704103559755006.590468055872140.787436871755226.208523555
872461.099936919755300.861301319872688.327786427755241.248008847
872918.431408343754927.221849234873056.021818131 754816.94310811
873766.958842638754485.076248574874120.835229251 754378.82032149

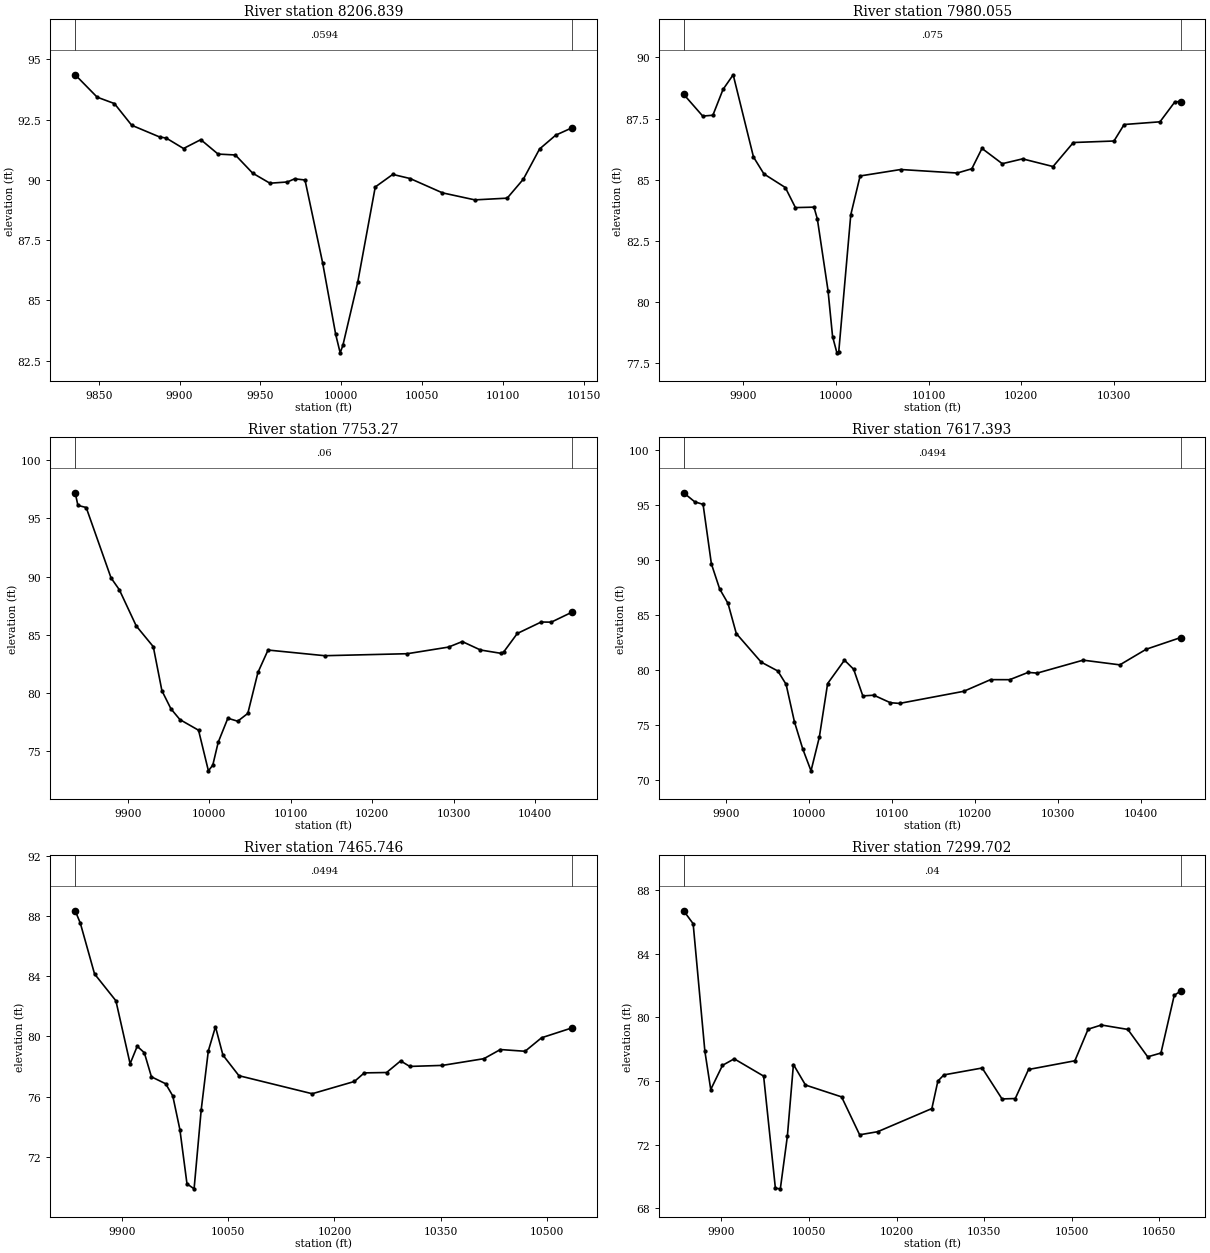
Type RM Length L Ch R = 1 ,8206.839,226.784100,226.784100,226.784100
XS GIS Cut Line= 6
866856.571258757753887.698335405866900.014820677753772.546531902
866915.958235059753735.298659211866916.828527348753733.497939517
866932.406066739753696.100713184866928.216992429753594.868021926
#Sta/Elev= 30
9835.40994.364789848.981  93.4369859.66993.169749870.35792.269729887.61791.78353
9891.73391.737149902.42191.304489913.10991.671849923.797 91.07299934.485 91.0357
9945.17390.282449955.86189.863499966.69289.915049971.15290.04586 9977.5789.99773
9988.44786.570849996.56583.587869999.33282.82227   1000183.1304310010.2185.75908
10021.0489.7074310031.87  90.22910042.6190.0577310062.6389.4632410082.6589.17179
10102.6689.2433910112.6790.0321110122.6891.2836710132.6991.8580610142.8392.16547
#Mann= 3 , 0 , 0
9835.409  0.0594       09835.409  0.0594       010142.83  0.0594       0
#XS Ineff= 2 , 0
       0                10027.99       0
Bank Sta=9835.409,10142.83
Exp/Cntr=0.3,0.1

Type RM Length L Ch R = 1 ,7980.055,226.784100,226.784100,226.784100
XS GIS Cut Line= 6
867051.845444445753963.789314564867084.604257908753891.012335757
867126.337151092753818.410604668867127.410902081 753816.72328179
867139.000529401753797.003743859866995.867065594753479.419930595
#Sta/Elev= 30
9835.44988.494899856.05487.60401 9867.02 87.63879877.98688.693129888.95389.29228
9910.88585.931339922.19385.238319945.26284.684119956.18583.863859976.25183.88175
9979.86583.39963  9991.480.473949996.31778.59322   1000177.92706   1000377.97639
10015.9883.5699410026.0785.1566810069.9585.4204810130.9685.2761510146.7385.45096
 10157.7 86.282110179.6385.6581210201.5785.8552910234.4885.5414610256.41 86.5236
10300.2986.5853310311.2687.2596410349.9987.37012 10366.188.1869210372.2288.19623
#Mann= 3 , 0 , 0
9835.449   0.075       09835.449   0.075       010372.22   0.075       0
#XS Ineff= 2 , 0
       0                10022.35       0
Bank Sta=9835.449,10372.22
Exp/Cntr=0.3,0.1

Type RM Length L Ch R = 1 , 7753.27,135.877800,135.877800,135.877800
XS GIS Cut Line= 6
 867379.84650261754008.280023382867369.320683149753950.103894471
867356.141760223753906.972303804867339.735485475753872.158350821
867310.368674373753827.833017563867065.148176309753494.416363192
#Sta/Elev= 30
9835.51497.185499838.84796.10168 9849.0195.921869879.49789.882229889.65988.86732
9910.42885.759569931.34183.980699941.91580.20232 9952.9778.652099964.02577.72496
9986.877 76.8122 9998.9773.3281710004.36 73.818910010.9975.7780610022.8477.84199
10034.9277.5852910047.3378.2564310059.7581.7704910072.1683.6917710141.7383.20643
   1024383.3773810293.6383.9460110310.51 84.419710332.8483.6961510357.6783.41358
10361.1583.5114610378.0285.1138210407.3286.0963210419.7386.0865310445.2986.94585
#Mann= 3 , 0 , 0
9835.514    0.06       09835.514    0.06       010445.29    0.06       0
#XS Ineff= 2 , 0
       0                10085.55       0
Bank Sta=9835.514,10445.29
Exp/Cntr=0.3,0.1

Type RM Length L Ch R = 1 ,7617.393,151.646700,151.646700,151.646700
XS GIS Cut Line= 3
867454.417801114753958.396648255867451.337459564753767.651050141
867277.364636749753398.863516032
#Sta/Elev= 30
9848.96496.138459862.36395.314249872.36495.085939882.36589.682469892.36687.39318
9902.368 86.08679912.36983.344769942.37380.743459962.37679.939479972.37778.72474
9982.378 75.32889992.379 72.863410002.3870.8630410012.3873.9188910022.3878.79701
10042.6780.9219410053.7280.0989510064.78 77.674510078.0377.7382210097.9577.05545
10109.0176.99248 10186.478.0944810218.6679.1526510241.6979.14918 10263.8 79.8086
10274.8679.7482310330.1480.9235710374.3780.4966510406.1681.91849 10447.582.97458
#Mann= 3 , 0 , 0
9848.964  0.0494       09848.964  0.0494       0 10447.5  0.0494       0
#XS Ineff= 2 , 0
       0                10054.48       0
Bank Sta=9848.964,10447.5
Exp/Cntr=0.3,0.1

Type RM Length L Ch R = 1 ,7465.746,166.043600,166.043600,166.043600
XS GIS Cut Line= 4
867588.047079944753982.221226567867605.626727286753786.481933887
 867524.81664368753535.561602513867401.405603056753327.902945787
#Sta/Elev= 30
 9834.0588.35943  9841.387.533959861.381 84.15679891.50182.374969911.58278.18298
9921.62279.347139931.66278.915639941.70377.313229961.78376.852059971.82376.04519
9981.86473.806429991.90470.1935510001.9469.8614310011.9875.1153810022.0279.03483
10032.1380.6466510042.6478.7597510065.2477.3886510168.7176.1886710228.3577.00498
10242.2577.5751610273.7777.5998510293.5978.3723610306.4778.0049610352.55 78.0734
10411.1778.5202510434.4379.1284710469.3379.01311 10492.679.9114210535.7580.57107
#Mann= 3 , 0 , 0
 9834.05  0.0494       0 9834.05  0.0494       010535.75  0.0494       0
#XS Ineff= 2 , 0
       0                   10029       0
Bank Sta=9834.05,10535.75
Exp/Cntr=0.3,0.1

Type RM Length L Ch R = 1 ,7299.702,177.178500,177.178500,177.178500
XS GIS Cut Line= 6
867785.615478865753991.197342375 867775.56916375753887.241760326
867767.459105113753826.625635022867760.733442298753802.314916037
867692.773739565753530.839319675 867513.27092416753195.373923537
#Sta/Elev= 30
9835.40486.686829851.67785.87411 9871.7777.864699881.81675.464479901.90976.98096
9922.00377.391689972.371 76.30739992.54869.26556   1000169.2284310013.0672.53487
10023.4477.0345710044.0775.7459710105.92  75.00210136.8572.6215510167.7872.81587
10260.5574.2685710270.8675.9961110281.1776.3821510346.7276.8153310380.7574.87282
10403.4374.8984410426.1276.7222910505.5177.2690710528.1979.2524510550.8779.51504
10596.2479.2369410630.2677.5174210652.9577.7558410675.6381.3681210686.5581.65604
#Mann= 3 , 0 , 0
9835.404    0.04       09835.404    0.04       010686.55    0.04       0
#XS Ineff= 2 , 0
       09961.962        10033.92       0
Bank Sta=9835.404,10686.55
Exp/Cntr=0.3,0.1

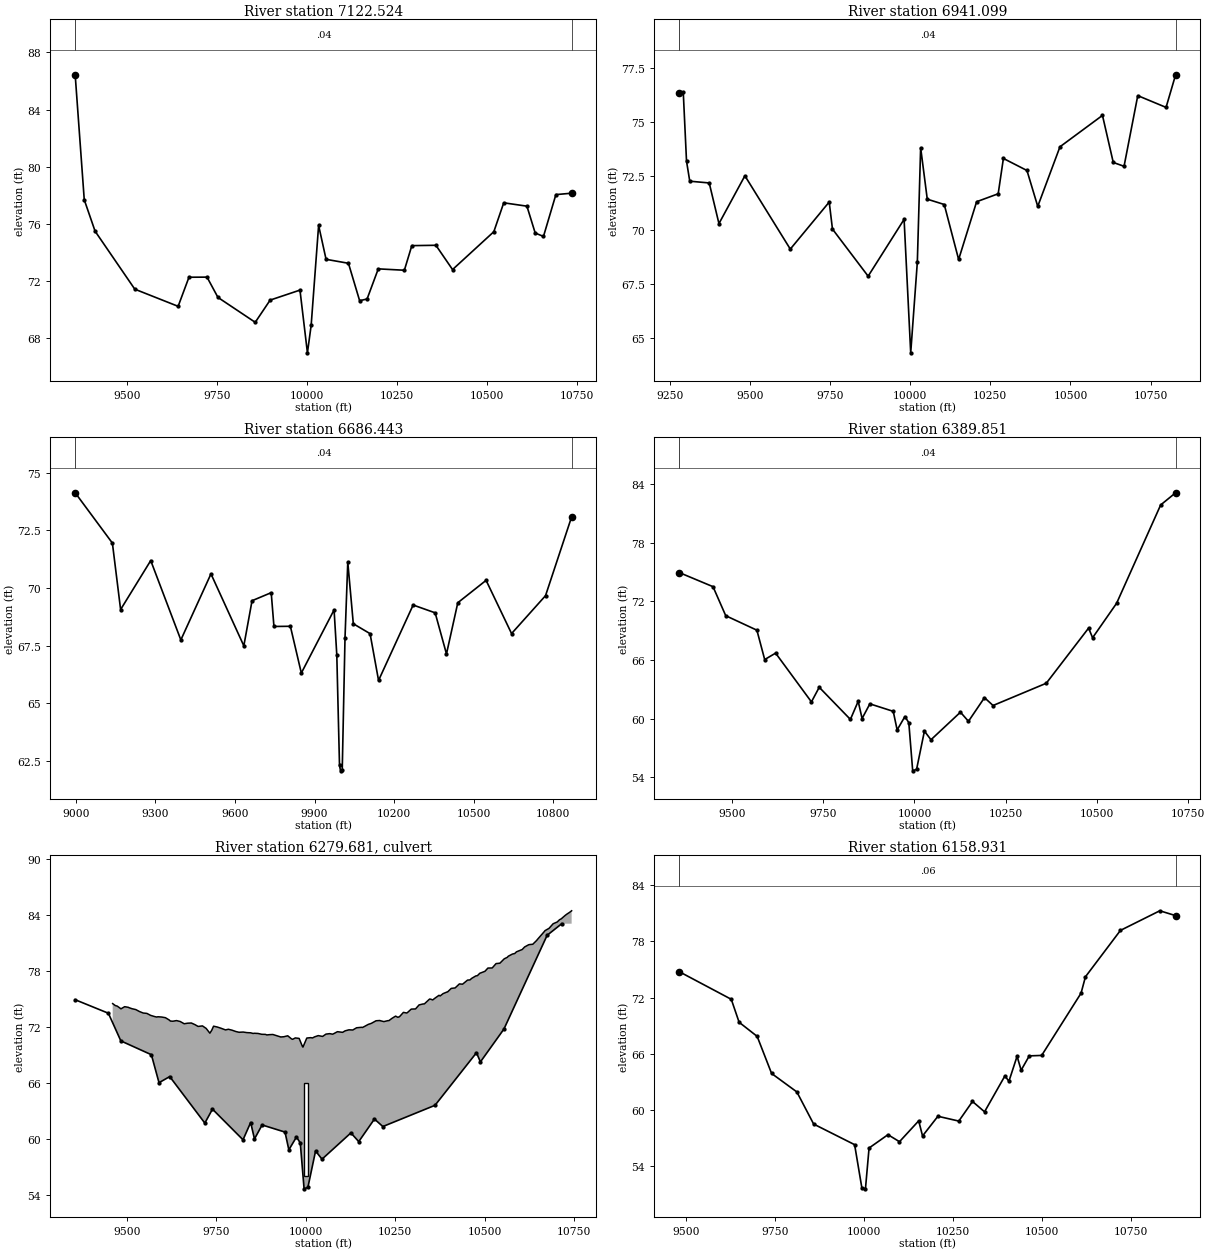
Type RM Length L Ch R = 1 ,7122.524,181.424800,181.424800,181.424800
XS GIS Cut Line= 4
868036.568904531754430.128165457868008.143675556754043.642754235
867861.399407855753496.788717883867652.160896051 753126.92409734
#Sta/Elev= 30
9355.40686.432519380.60277.692059410.68375.49426 9520.9871.439169641.30570.23988
9671.38672.274439721.52172.282149751.88470.863299855.42269.122379896.83770.67545
9979.66771.3749310000.3766.9874910010.7368.9110410031.4475.8988310052.1473.52671
10114.2773.2508510145.33 70.633710166.0470.75316 10197.172.8597510269.5772.76364
10290.2874.4842310357.15 74.509210403.3772.81028   1051875.4583710545.5377.47937
10609.9177.2444710632.8975.3653710655.8775.1274310690.3478.0527210734.0878.15143
#Mann= 3 , 0 , 0
9355.406    0.04       09355.406    0.04       010734.08    0.04       0
#XS Ineff= 2 , 0
       09963.806        10030.53       0
Bank Sta=9355.406,10734.08
Exp/Cntr=0.3,0.1

Type RM Length L Ch R = 1 ,6941.099,254.655600,254.655600,254.655600
XS GIS Cut Line= 6
868234.528784838754467.704244856868134.478686176753818.292689273
868115.813326968753745.229475425868115.296544887753743.297395022
868096.221151874753669.938970426 867761.49367465753011.614610474
#Sta/Elev= 30
9279.25176.357299292.10576.368889302.22373.189429312.341 72.26179373.04972.18044
9403.402 70.30029484.34672.511429625.99869.120819747.41471.296979757.53270.04765
 9868.8367.868449981.00770.4967910001.6564.3231210022.31  68.51510032.64 73.8116
 10053.371.4300210106.2971.1837410151.1668.6407510207.26 71.312410274.5771.68001
 10290.873.3136610364.3172.7568810397.9771.0972810467.3173.85336 10599.975.30501
10633.5673.1290110667.2172.9501110710.0176.2193210798.27 75.674810828.0777.18352
#Mann= 3 , 0 , 0
9279.251    0.04       09279.251    0.04       010828.07    0.04       0
#XS Ineff= 2 , 0
       09968.484        10036.86       0
Bank Sta=9279.251,10828.07
Exp/Cntr=0.3,0.1

Type RM Length L Ch R = 1 ,6686.443,296.591900,296.591900,296.591900
XS GIS Cut Line= 6
868610.121118367 754660.92180394868378.177220666753754.524052464
868365.175474759753693.111423603868364.855330548753691.137213587
868340.848968411753609.957137763868066.808048127752872.756668675
#Sta/Elev= 30
8997.61874.129799137.91971.946139168.88669.06187 9282.4371.188069395.97567.74336
9509.51970.610229633.38667.487689664.35269.445439736.60869.79464 9746.9368.32763
9808.86468.335979850.15266.305359973.62269.047639983.84367.095119994.06562.29742
9997.99562.06237 10004.4 62.118310014.82 67.831610025.2571.1192310046.1168.44573
10109.2868.0161410141.2865.9860810271.63 69.258710354.6568.9196610397.3367.13545
   1044069.3577410546.6970.32954 10642.768.0198610770.7369.6647410869.1473.08595
#Mann= 3 , 0 , 0
8997.618    0.04       08997.618    0.04       010869.14    0.04       0
#XS Ineff= 2 , 0
       09957.892        10031.74       0
Bank Sta=8997.618,10869.14
Exp/Cntr=0.3,0.1

Type RM Length L Ch R = 1 ,6389.851,230.920100,230.920100,230.920100
XS GIS Cut Line= 4
868877.467946947754224.563737104868663.960011585753652.874944934
 868644.70924868753600.122336535 868359.21066599752967.665135486
#Sta/Elev= 30
9355.25574.935149448.05673.487689482.88570.521759568.28269.039639589.63166.03879
9619.55166.696499717.72761.709999739.07663.205059824.47359.919079845.82361.77183
9856.49760.011979877.84761.510679941.89560.745119952.56958.845649973.895 60.2154
 9984.5459.583019995.185 54.663610005.8354.8178110027.2958.7238410045.2757.84203
10126.0360.6596710147.98 59.726510191.8662.14379 10215.461.3417210361.2363.61827
10477.1369.25414 10488.168.2677610553.9371.7936910674.6281.8411110715.5883.08602
#Mann= 3 , 0 , 0
9355.255    0.04       09355.255    0.04       010715.58    0.04       0
#XS Ineff= 2 , 0
       09972.983           10034       0
Bank Sta=9355.255,10715.58
Exp/Cntr=0.3,0.1

Type RM Length L Ch R = 2 ,6279.681,,,
Bridge Culvert--1,0,-1,-1, 0
Deck Dist Width WeirC Skew NumUp NumDn MinLoCord MaxHiCord MaxSubmerge Is_Ogee
15.46,200,2.6,0,171,171, , , 0.95, 0, 0,0,,
 9460.05 9462.55 9467.40 9472.90 9483.26 9493.61 9503.97 9505.91 9514.32 9524.68
 9535.03 9544.42 9545.39 9555.74 9566.10 9576.45 9582.94 9586.81 9597.17 9607.52
 9617.88 9621.45 9628.23 9638.59 9648.94 9659.30 9659.96 9669.65 9680.01 9690.36
 9698.47 9700.72 9711.07 9721.43 9731.78 9736.98 9742.14 9752.49 9762.85 9773.20
 9775.49 9783.56 9793.91 9804.27 9814.00 9814.62 9824.98 9835.34 9845.69 9852.51
 9856.05 9866.40 9876.76 9887.11 9891.02 9897.47 9907.82 9918.18 9928.53 9929.53
 9938.89 9949.24 9949.81 9959.93 9963.04 9970.64 9981.35 9990.99 9992.0610002.77
10013.4810018.9410024.1810034.8910045.6010046.9010056.3110067.0210074.8510077.73
10088.4410099.1510102.8010109.8510120.5610130.7510131.2710141.9810152.6910155.64
10158.3510163.5610174.5010183.0810185.4310196.3610207.3010207.8110218.2310229.16
10232.5410240.1010251.0310257.2810261.9610272.9010282.0110283.8310294.7710305.70
10306.7410316.6310327.5710331.4710338.5010346.0810349.5710354.6210360.9710372.36
10375.4810383.7610395.1510396.3410406.5510417.2110417.9410429.3310438.0710440.73
10452.1210458.9310463.5210474.9110479.7910486.3110497.7010500.6610509.0910520.49
10521.5210531.8810542.3810543.2810554.6710563.2410566.0710577.4610584.1110588.85
10600.2510604.9710611.6410623.0410625.8310634.4310645.8310646.6910657.2210667.56
10668.6110680.0110688.4210691.4010702.8010709.2810714.1910725.5810730.1410736.98
10743.14
   74.52   74.45   74.31   74.25   73.96   74.19   74.12   74.08   73.97   73.88
   73.67   73.52   73.51   73.47   73.26   73.14   73.08   73.11   73.08   73.01
   72.77   72.65   72.63   72.70   72.60   72.37   72.36   72.42   72.44   72.26
   72.08   72.08   72.13   71.86   71.35   71.66   72.10   72.01   71.88   71.73
   71.70   71.77   71.67   71.53   71.44   71.45   71.47   71.41   71.39   71.32
   71.34   71.32   71.23   71.22   71.16   71.19   71.21   71.09   70.96   70.94
   70.97   71.07   71.06   70.74   70.69   70.84   70.79   69.89   69.86   70.83
   70.87   70.84   70.95   71.09   71.00   71.00   71.25   71.30   71.24   71.29
   71.51   71.46   71.44   71.60   71.71   71.69   71.69   71.93   71.96   71.98
   71.96   72.06   72.29   72.40   72.45   72.68   72.71   72.69   72.59   72.69
   72.70   72.92   73.18   73.05   73.12   73.58   73.51   73.55   73.93   73.94
   73.95   74.38   74.48   74.49   74.74   75.01   74.99   74.91   75.10   75.41
   75.34   75.59   75.77   75.77   76.15   76.20   76.22   76.63   76.60   76.68
   77.04   77.06   77.22   77.48   77.52   77.77   77.94   77.98   78.33   78.34
   78.36   78.81   78.85   78.88   79.32   79.48   79.60   79.83   79.89   80.07
   80.25   80.32   80.59   80.83   80.85   80.88   81.31   81.36   81.82   82.28
   82.34   82.59   82.96   83.08   83.27   83.51   83.61   83.99   84.12   84.29
   84.47
                                                                                
                                                                                
                                                                                
                                                                                
                                                                                
                                                                                
                                                                                
                                                                                
                                                                                
                                                                                
                                                                                
                                                                                
                                                                                
                                                                                
                                                                                
                                                                                
                                                                                
        
 9460.05 9462.55 9467.40 9472.90 9483.26 9493.61 9503.97 9505.91 9514.32 9524.68
 9535.03 9544.42 9545.39 9555.74 9566.10 9576.45 9582.94 9586.81 9597.17 9607.52
 9617.88 9621.45 9628.23 9638.59 9648.94 9659.30 9659.96 9669.65 9680.01 9690.36
 9698.47 9700.72 9711.07 9721.43 9731.78 9736.98 9742.14 9752.49 9762.85 9773.20
 9775.49 9783.56 9793.91 9804.27 9814.00 9814.62 9824.98 9835.34 9845.69 9852.51
 9856.05 9866.40 9876.76 9887.11 9891.02 9897.47 9907.82 9918.18 9928.53 9929.53
 9938.89 9949.24 9949.81 9959.93 9963.04 9970.64 9981.35 9990.99 9992.0610002.77
10013.4810018.9410024.1810034.8910045.6010046.9010056.3110067.0210074.8510077.73
10088.4410099.1510102.8010109.8510120.5610130.7510131.2710141.9810152.6910155.64
10158.3510163.5610174.5010183.0810185.4310196.3610207.3010207.8110218.2310229.16
10232.5410240.1010251.0310257.2810261.9610272.9010282.0110283.8310294.7710305.70
10306.7410316.6310327.5710331.4710338.5010346.0810349.5710354.6210360.9710372.36
10375.4810383.7610395.1510396.3410406.5510417.2110417.9410429.3310438.0710440.73
10452.1210458.9310463.5210474.9110479.7910486.3110497.7010500.6610509.0910520.49
10521.5210531.8810542.3810543.2810554.6710563.2410566.0710577.4610584.1110588.85
10600.2510604.9710611.6410623.0410625.8310634.4310645.8310646.6910657.2210667.56
10668.6110680.0110688.4210691.4010702.8010709.2810714.1910725.5810730.1410736.98
10743.14
   74.52   74.45   74.31   74.25   73.96   74.19   74.12   74.08   73.97   73.88
   73.67   73.52   73.51   73.47   73.26   73.14   73.08   73.11   73.08   73.01
   72.77   72.65   72.63   72.70   72.60   72.37   72.36   72.42   72.44   72.26
   72.08   72.08   72.13   71.86   71.35   71.66   72.10   72.01   71.88   71.73
   71.70   71.77   71.67   71.53   71.44   71.45   71.47   71.41   71.39   71.32
   71.34   71.32   71.23   71.22   71.16   71.19   71.21   71.09   70.96   70.94
   70.97   71.07   71.06   70.74   70.69   70.84   70.79   69.89   69.86   70.83
   70.87   70.84   70.95   71.09   71.00   71.00   71.25   71.30   71.24   71.29
   71.51   71.46   71.44   71.60   71.71   71.69   71.69   71.93   71.96   71.98
   71.96   72.06   72.29   72.40   72.45   72.68   72.71   72.69   72.59   72.69
   72.70   72.92   73.18   73.05   73.12   73.58   73.51   73.55   73.93   73.94
   73.95   74.38   74.48   74.49   74.74   75.01   74.99   74.91   75.10   75.41
   75.34   75.59   75.77   75.77   76.15   76.20   76.22   76.63   76.60   76.68
   77.04   77.06   77.22   77.48   77.52   77.77   77.94   77.98   78.33   78.34
   78.36   78.81   78.85   78.88   79.32   79.48   79.60   79.83   79.89   80.07
   80.25   80.32   80.59   80.83   80.85   80.88   81.31   81.36   81.82   82.28
   82.34   82.59   82.96   83.08   83.27   83.51   83.61   83.99   84.12   84.29
   84.47
                                                                                
                                                                                
                                                                                
                                                                                
                                                                                
                                                                                
                                                                                
                                                                                
                                                                                
                                                                                
                                                                                
                                                                                
                                                                                
                                                                                
                                                                                
                                                                                
                                                                                
        
BR Coef=-1 , 0 , 0 ,, 0 ,,,0.8,-1,,0,
WSPro=,,,, 1 ,,,, 0 ,,,, 0 ,,,,-1 ,-1 ,-1 , 0 , 0 , 0 , 0 , 0
Culvert=2,10,10,200,0.013,0.5,1,8,3,56,10000,52,10000,Culvert #1, 0, 15.46
Culvert Bottom n=0.013
BC Design=,, 0 ,, 0 ,,,,,,

Type RM Length L Ch R = 1 ,6158.931,385.995300,385.995300,385.995300
XS GIS Cut Line= 6
868970.312965258754161.104825432868885.610643478753677.898972695
868875.482358926753621.464655132868767.756950831753358.571679636
868680.692002651753201.604125817 868456.38630945752888.891251838
#Sta/Elev= 30
9480.227 74.75659626.83371.808359648.86469.362719699.627 67.85829740.23663.90538
9811.30461.936289858.50258.514279973.745 56.31699994.06551.7252410004.2251.61046
10014.3855.9601210067.5457.3808710099.9656.63318   10154 58.857410164.8157.24573
10208.0359.3443510266.7758.83145 10305.360.92141 10339.2 59.818810396.38 63.6388
10407.81 63.078310430.6865.7378210442.12 64.253410464.9965.7789810499.8765.82806
10610.6372.4600910622.9374.2056910721.39 79.150810832.1481.2417410876.5880.72558
#Mann= 3 , 0 , 0
9480.227    0.06       09480.227    0.06       010876.58    0.06       0
#XS Ineff= 2 , 0
       09969.326        10034.51       0
Bank Sta=9480.227,10876.58
Exp/Cntr=0.3,0.1

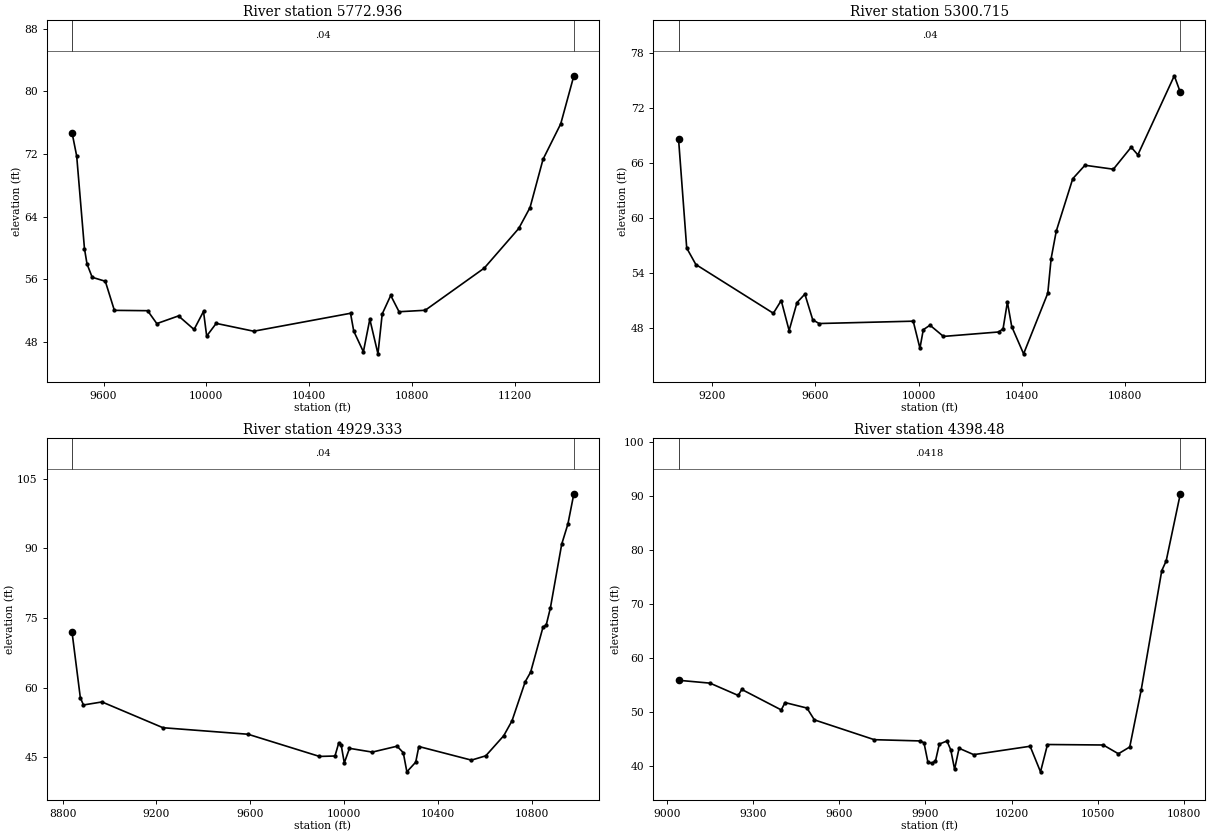
Type RM Length L Ch R = 1 ,5772.936,472.221200,472.221200,472.221200
XS GIS Cut Line= 6
  868976.0429749754176.860339677869027.213342182754087.602812009
869163.239836223 753870.93250283869357.950370188753596.341943456
869690.237314123753153.148575254870126.233925045752600.045473981
#Sta/Elev= 30
9477.41574.712399495.42571.742259525.66759.910769535.63757.944879555.74456.24896
 9606.8555.73906 9642.0952.02156 9771.5251.978229807.38150.329169891.822  51.311
9952.42349.57572 9989.1451.8870410001.4948.7339510038.5650.3560910184.57 49.3545
10561.5451.6480110574.0349.3702110611.5846.7249710636.6550.8842510668.3146.46349
10684.8951.5627210718.0553.9275710750.4251.8448710852.2152.0317311082.3457.42608
11216.4862.4908111260.4465.1660711311.0171.3298211379.9775.8665611431.03 82.0046
#Mann= 3 , 0 , 0
9477.415    0.04       09477.415    0.04       011431.03    0.04       0
#XS Ineff= 2 , 0
       09976.972        10161.87       0
Bank Sta=9477.415,11431.03
Exp/Cntr=0.3,0.1

Type RM Length L Ch R = 1 ,5300.715,371.382200,371.382200,371.382200
XS GIS Cut Line= 6
 869114.22744817754545.614407901869567.352812578754024.287951133
869908.385108941753608.552376611870004.070058512753472.424731179
870059.967803787753399.828695361870349.829178979753048.197529796
#Sta/Elev= 30
9071.01868.662699102.68256.748339138.07954.953189438.04249.636879468.52951.02773
9499.01747.752349529.50450.800669559.99151.727119590.47848.923119615.05848.51825
9979.40948.7742210005.3845.8238110018.37 47.842310044.3548.33611 10096.3 47.1119
10310.5347.5979410327.2347.9585810343.9250.8558610360.6748.1868610406.5945.21197
10500.2351.8230710513.1555.5955810533.0158.59209 10596.964.3127810644.0665.77911
10754.1165.3477110822.9967.7508710848.91 66.912710989.9375.5376711013.2573.73912
#Mann= 3 , 0 , 0
9071.018    0.04       09071.018    0.04       011013.25    0.04       0
#XS Ineff= 2 , 0
       09827.709        10257.15       0
Bank Sta=9071.018,11013.25
Exp/Cntr=0.3,0.1

Type RM Length L Ch R = 1 ,4929.333,530.852700,530.852700,530.852700
XS GIS Cut Line= 2
869168.392921349754758.460449445 870784.19965752753359.428752075
#Sta/Elev= 30
 8840.6871.914568875.87557.840178889.10256.275228968.18456.927339227.89451.37176
9590.16249.966559894.39645.187169960.53445.276529976.47348.080179986.98947.62774
10000.2243.79455 10022.346.9330910119.2646.1185810225.0847.3919610251.46  45.987
10266.74 41.865810304.4543.9555610317.6847.3232910541.7344.3880710602.8345.31984
10679.2249.64116 10714.552.8549210770.8861.2951810793.8763.3409410846.7873.08029
10860.0173.4622610877.8277.1283310926.1490.90821 10952.695.26371   10978101.7845
#Mann= 3 , 0 , 0
 8840.68    0.04       0 8840.68    0.04       0   10978    0.04       0
#XS Ineff= 2 , 0
       09722.249        10165.76       0
Bank Sta=8840.68,10978
Exp/Cntr=0.3,0.1

Type RM Length L Ch R = 1 , 4398.48,0.000000,0.000000,0.000000
XS GIS Cut Line= 6
869833.050360609755099.508288946869915.391703501754965.272719293
870073.728422988754755.078292329870549.339025399754203.210690034
870676.461642731754033.455492752870927.094515209753741.395756658
#Sta/Elev= 30
9040.45655.913389150.05955.384219248.20953.107989260.57154.219899398.06450.42674
9411.24851.788859487.51850.777169513.331 48.58969721.89844.925289881.64744.69266
9894.95944.347159908.27240.850519921.58440.532499934.89740.977589948.20944.11052
9974.83444.679719988.14643.0427410001.4639.45416   1001743.3384710068.0242.15751
10264.4243.7083810300.5938.9758810324.85 44.031110518.9743.9417710571.6842.32082
10611.2143.5771510650.7454.0286410722.6376.1928510737.9877.9868110787.2790.41477
#Mann= 3 , 0 , 0
9040.456  0.0418       09040.456  0.0418       010787.27  0.0418       0
#XS Ineff= 2 , 0
       09970.831        10261.76       0
Bank Sta=9040.456,10787.27
Exp/Cntr=0.3,0.1